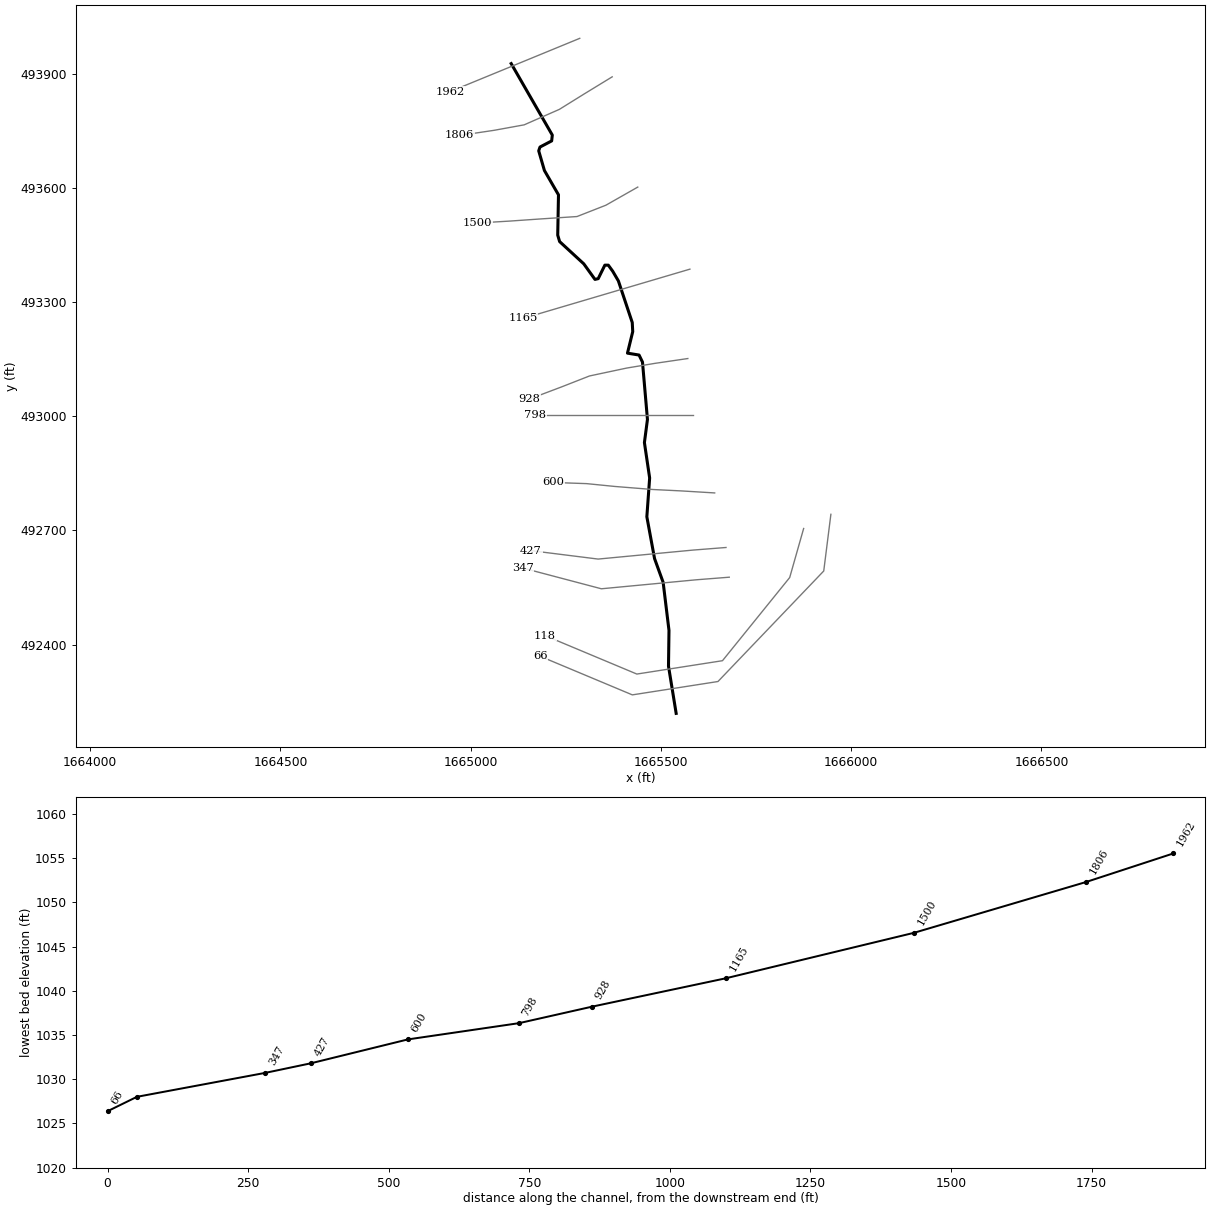
--- NFGraveCkT1.prj (project) ---

Proj Title=NFGraveCkT1
Current Plan=p01
Default Exp/Contr=0.3,0.1
English Units
Geom File=g01
Flow File=f01
Plan File=p01
Y Axis Title=Elevation
X Axis Title(PF)=Main Channel Distance
X Axis Title(XS)=Station
BEGIN DESCRIPTION:
---------- MODELED AS PART OF WVEM CTP PROGRAM, 2025----------
Stream Name: North Fork Grave Creek Tributary 1
Flood Zone: AFH
Marshall County, WV
HEC-RAS Version: RAS 6.6
Vertical Datum: NAVD88
Projection: NAD 1983 StatePlane West Virginia N FIPS 4701 (US Feet)
Terrain: 1-meter West Virginia FEMA R3 South Central (collected 2018-2019)
Land Use: 2024 NLCD
Hydrologic Method:
Duda et al., "Estimation of magnitude and frequency of floods for rural, unregulated streams in and near Virginia and West Virginia." September 8, 2025.
Additional Model Notes:
None
END DESCRIPTION:
DSS Export Rating Curves= 0
DSS Export Rating Curve Sorted= 0
DSS Export Volume Flow Curves= 0
DXF OffsetX= 0
DXF OffsetY= 0
DXF ScaleX= 1
DXF ScaleY= 10

--- NFGraveCkT1.p01 (plan) ---

Plan Title=Floodplain
Program Version=6.60
Short Identifier=Floodplain
Geom File=g01
Flow File=f01
Subcritical Flow
K Sum by GR= 0
Std Step Tol= 0.01
Critical Tol= 0.01
Num of Std Step Trials= 20
Max Error Tol= 0.3
Flow Tol Ratio= 0.001
Split Flow NTrial= 30
Split Flow Tol= 0.02
Split Flow Ratio= 0.02
Log Output Level= 0
Friction Slope Method= 1
Unsteady Friction Slope Method= 2
Unsteady Bridges Friction Slope Method= 1
Parabolic Critical Depth
Global Vel Dist= 0 , 0 , 0
Global Log Level= 0
CheckData=True
Encroach Param=-1 ,0,0, 0
Flow Ratio Tolerance=0.1
Flow Ratio Min Ratio=0.5
Flow Ratio Max Ratio=4
Flow Ratio Max Iterations= 10
Computation Interval=1MIN
Output Interval=1HOUR
Instantaneous Interval=1HOUR
Mapping Interval=1HOUR
Computation Time Step Use Courant=        0
Computation Time Step Use Time Series=    0
Computation Time Step Count To Double=0
Computation Time Step Max Doubling=0
Computation Time Step Max Halving=0
Computation Time Step Residence Courant=0
Run HTab= 0
Run UNet= 0
Run Sediment= 0
Run PostProcess= 0
Run WQNet= 0
Run RASMapper=-1
UNET Theta= 1
UNET Theta Warmup= 1
UNET ZTol= 0.02
UNET ZSATol= 0.02
UNET MxIter= 20
UNET Max Iter WO Improvement= 0
UNET MaxInSteps= 0
UNET DtIC= 0
UNET DtMin= 0
UNET MaxCRTS= 20
UNET WFStab= 2
UNET SFStab= 1
UNET WFX= 1
UNET SFX= 1
UNET Gravity=32.17405
UNET 1D Methodology=Finite Difference
UNET DSS MLevel= 4
UNET Pardiso=0
UNET DZMax Abort= 100
UNET Use Existing IB Tables=-1
UNET Froude Reduction=False
UNET Froude Limit= 0.8
UNET Froude Power= 4
UNET D1 Cores= 0
UNET WindReference=Eulerian
UNET WindDragFormulation=Hsu (1988)
UNET D2 Coriolis=0
UNET D2 Cores= 0
UNET D2 Theta= 1
UNET D2 Theta Warmup= 1
UNET D2 Z Tol= 0.01
UNET D2 Volume Tol= 0.01
UNET D2 Max Iterations= 20
UNET D2 Advanced Convergence=0
UNET D2 WS Max Tol=0.15
UNET D2 WS RMS Tol=0.002
UNET D2 WS Stall Tol=1
UNET D2 Equation= 0
UNET D2 RampUpFraction=0.1
UNET D2 TimeSlices= 1
UNET D2 Turbulence Formulation=None
UNET D2 Eddy Viscosity=0.3
UNET D2 Transverse Eddy Viscosity=0.1
UNET D2 Smagorinsky Mixing=0.05
UNET D2 BCVolumeCheck=0
UNET D2 Cores=0
UNET D2 SolverType=PARDISO (Direct)
UNET D2 Minimum Iterations= 3
UNET D2 Maximum Iterations= 30
UNET D2 Restart Number= 10
UNET D2 Relaxation Coeff=1.3
UNET D2 SOR Precondition Iterations= 10
UNET D2 ILUT Maximum Fill= 8
UNET D2 ILUT Tolerance=1E-08
UNET D2 Convergence Tolerance=0.00001
PS Theta= 1
PS WS Tol= 0.01
PS Volume Tol= 0.01
PS Max Iterations= 20
PS Equation= 0
PS Advance Time Step=-1
PS Target Courant=0.9
PS Time Slices= 1
PS Iterate With 2D=0
PS Project Initial WSE from DS=-1
PS Ramp Up Initial WSE from US=-1
PS Cores=0
UNET D1D2 MaxIter= 0
UNET D1D2 ZTol=0.01
UNET D1D2 QTol=0.1
UNET D1D2 MinQTol=1
Write IC File= 0
Write IC File at Fixed DateTime=0
Write IC File at Sim End=0
Echo Input=False
Echo Parameters=False
Echo Output=False
Write Detailed= 0
HDF Write Warmup=0
HDF Write Time Slices=0
HDF Flush=0
HDF Compression= 1
HDF Chunk Size= 1
HDF Spatial Parts= 1
HDF Use Max Rows=0
HDF Fixed Rows= 1
Calibration Method= 0
Calibration Iterations= 20
Calibration Max Change=0.05
Calibration Tolerance=0.2
Calibration Maximum=1.5
Calibration Minimum=0.5
Calibration Optimization Method= 1
WQ AD Non Conservative
WQ ULTIMATE=-1
WQ Max Comp Step=1HOUR
WQ Output Interval=15MIN
WQ Output Selected Increments= 0
WQ Create Restart=0
WQ Fixed Restart=0
WQ System Summary=0
WQ Write To DSS=0
Sorting and Armoring Iterations= 10
XS Update Threshold= 0.02
Bed Roughness Predictor= 0
Processes Affected by Predictor=Sediment Only
Hydraulics Update Threshold= 0.02
Energy Slope Method= 1
Volume Change Method= 1
Sediment Retention Method= 0
Sediment TS Multiplier= 1
Warm Up Method= 0
XS Weighting Method= 0
Number of US Weighted Cross Sections= 1
Number of DS Weighted Cross Sections= 1
Upstream XS Weight=0
Main XS Weight=1
Downstream XS Weight=0
Number of DS XS's Weighted with US Boundary= 1
Upstream Boundary Weight= 1
Weight of XSs Associated with US Boundary= 0
Number of US XS's Weighted with DS Boundary= 1
Downstream Boundary Weight= 0.5
Weight of XSs Associated with DS Boundary= 0.5
Percentile Method= 0
Sediment Output Level= 3
Mass or Volume Output= 0
Output Increment Type= 1
Profile and TS Output Increment= 1
Transport Output Increment 1
XS Output Flag= 0
XS Output Increment= 10
Read HDF5 Sediment Hotstart= 0
Sediment Hotstart Type= 0
Write Gradation File= 0
Read Gradation Hotstart= 0
Write HDF5 File= 1
Write Binary Output= 1
Write DSS Sediment File= 0
DSS Sediment Output Type= 1
SV Curve= 0
Specific Gage Flag= 0
Subcell Erosion Methods= 0
Subcell Deposition Methods= 0
Advection Scheme= 1
Matrix Solver= 0
Implicit Weighting Factor= 1
Maximum Outer Loop Convergence Iterations= 5
Convergence Maximum Absolute= 0.001
Convergence RMSE= 0.0001
Grain Fractions Max Abs Error= 0.001
Max Subgrid Regions= 1
Max Subgrid Length Scale= 3.402823E+38
Initial Layer Thickness= 3
Min Layer Thickness= 0.1
Max Layer Thickness= 6
Number of Layers= 5

--- NFGraveCkT1.f01 (steady flow) ---

Flow Title=Flow
Program Version=6.60
Number of Profiles= 1
Profile Names=P100yr
River Rch & RM=NFGraveCkT1,Main            ,1962
     681
Boundary for River Rch & Prof#=NFGraveCkT1,Main            , 1
Up Type= 0
Dn Type= 3
Dn Slope=0.0028
DSS Import GetInterval= 0
DSS Import GetPeak= 0
DSS Import FillOption= 0

--- NFGraveCkT1.g01 (geometry) ---

Geom Title=Geometry
Program Version=6.60

River Reach=NFGraveCkT1     ,Main
Reach XY= 30
1665106.42649807493926.9942522271665214.45782472493739.162753731
1665212.75572839493723.8425743881665182.11536972493707.736635476
1665178.71084897493697.7852118161665193.73214439493646.055328399
1665230.69565314493582.1191045641665228.69762564493476.224303231
 1665233.6923663 493459.241397561665297.12924731493400.799585313
1665326.59998889493359.8403496441665335.09144172493361.838377148
 1665352.5740183 493397.302873151665361.63633613493397.274001807
1665373.15927897493381.4302014711665388.11889473 493355.88432081
1665424.56239139493246.5531746451665425.84126022493222.576844648
 1665412.0148443493166.0333225581665442.48459964493161.038253814
1665451.47572339493142.556663483 1665464.5226133492991.766610727
 1665456.5305033492931.0272308891665470.27686688492837.999857888
1665462.92419131492736.0213873091665483.16660489492626.191554472
1665505.76170406492563.7130048871665521.10648964492437.438651145
 1665519.8276208492343.4522905651665539.97062513492219.303260639

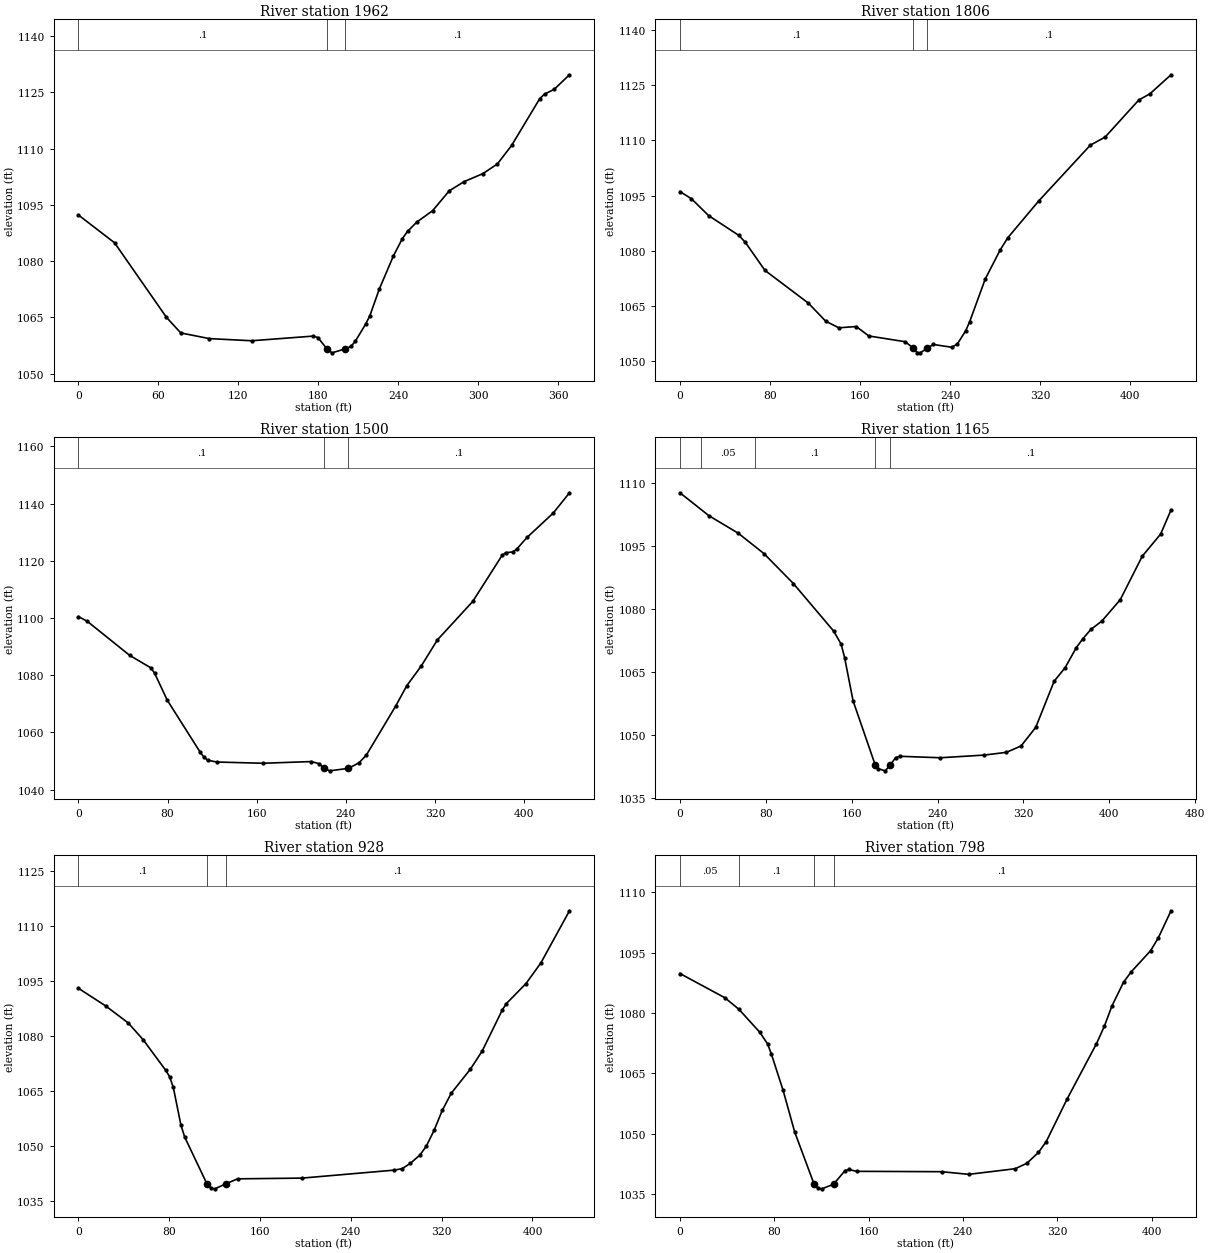
Type RM Length L Ch R = 1 ,1962    ,155.7,155.7,155.7
XS GIS Cut Line= 2
1665286.61019625493993.4172351291664945.76543308493853.337794307
#Sta/Elev= 30
       0 1092.28    27.1 1084.88    66.1 1064.98    76.8 1060.84    98.1 1059.33
     130 1058.75   176.1 1059.99   179.7 1059.61   186.5  1056.6   190.3 1055.53
   200.4  1056.6   204.5 1057.24   207.8 1058.62   215.5 1063.16   218.7 1065.41
   225.8 1072.53   236.4 1081.38   243.1 1085.98     247 1087.92   254.1 1090.44
   265.8 1093.42   278.3 1098.73   289.6  1101.2   303.5  1103.3   314.4 1105.88
   325.1 1110.83   346.2  1123.3   349.9 1124.53     357 1125.77 368.507 1129.66
#Mann= 3 ,-1,0
       0      .1       0   186.5    .045       0   200.4      .1       0
Bank Sta=186.5,200.4
XS Rating Curve= 0 ,0
Exp/Cntr(USF)=0,0
Exp/Cntr=0.3,0.1

Type RM Length L Ch R = 1 ,1806    ,305.6,305.8,299.1
XS GIS Cut Line= 6
1665371.88533142493892.257920012 1665296.9763605493846.481108665
1665233.05818126493806.7521855091665140.52326134493766.061978176
1665061.53949542493751.6968494211664970.78573993493738.163740009
#Sta/Elev= 30
       0 1096.11    10.2 1094.16    25.5 1089.57    52.4 1084.18    58.1 1082.31
    75.5 1074.69   114.1 1065.79   129.5 1060.88   141.1 1059.09   156.6 1059.44
   167.8 1056.87   200.1 1055.31  207.441053.518   210.8 1052.37   213.4 1052.29
  219.581053.516   225.1 1054.56   241.5  1053.8   246.4  1054.7   253.8 1058.27
   257.4 1060.79   271.2 1072.36   284.5 1080.27   291.2 1083.55   318.5 1093.49
   364.5 1108.71   377.7 1110.92   407.6 1120.99   417.5 1122.68   436.2 1127.84
#Mann= 3 ,-1,0
       0      .1       0  207.44    .045       0  219.58      .1       0
Bank Sta=207.44,219.58
XS Rating Curve= 0 ,0
Exp/Cntr(USF)=0,0
Exp/Cntr=0.3,0.1

Type RM Length L Ch R = 1 ,1500    ,326.9,334.6,332.8
XS GIS Cut Line= 6
1665439.08532825493602.4907830061665355.33976084493554.860957012
1665279.39503084493525.0791924151665179.61176585493518.489310592
1665104.79367401493513.2681924251665017.37947875493508.018202916
#Sta/Elev= 30
       0 1100.48       8 1098.81    45.9 1086.94    65.1 1082.52    68.4 1080.64
    79.7 1071.25     109 1053.21   112.5 1051.35   116.1 1050.25   124.2 1049.63
   165.4  1049.2     209 1049.79   215.6 1049.08  220.711047.425   225.4 1046.55
  242.231047.424   251.7 1049.35   258.3 1052.06   284.6 1069.19   294.6 1076.34
   307.6 1083.23     322 1092.31   353.7 1105.75     380 1121.83   383.3  1122.8
   389.8 1123.09   393.1 1124.02   402.4 1128.13     426 1136.68   440.5 1143.75
#Mann= 3 ,-1,0
       0      .1       0  220.71    .045       0  242.23      .1       0
Bank Sta=220.71,242.23
XS Rating Curve= 0 ,0
Exp/Cntr(USF)=0,0
Exp/Cntr=0.3,0.1

Type RM Length L Ch R = 1 ,1165    ,235.1,237.3,232.7
XS GIS Cut Line= 2
1665576.15541145493386.8156570381665137.39207879493257.220048035
#Sta/Elev= 30
       0 1107.72      27 1102.25    54.4 1098.06    78.3 1093.21   105.7 1086.07
   143.3 1074.71   150.2  1071.6   153.4 1068.42   161.3  1058.1  181.981042.765
   184.4 1041.95   191.2 1041.41  195.831042.766   200.9 1044.55   204.9 1044.88
   242.6 1044.53   283.6 1045.17   304.1 1045.82   317.8 1047.34   331.5 1051.79
   348.6 1062.77   358.9 1066.03   369.1 1070.73   375.2 1072.86   382.8 1075.12
   393.1 1077.13   410.2 1082.22   430.7 1092.59   447.8 1097.86   457.5 1103.62
#Mann= 5 ,-1,0
       0     .06       0      20     .05       0      70      .1       0
  181.98    .045       0  195.83      .1       0
Bank Sta=181.98,195.83
XS Rating Curve= 0 ,0
Exp/Cntr(USF)=0,0
Exp/Cntr=0.3,0.1

Type RM Length L Ch R = 1 ,928     ,131.4,130.2,128.7
XS GIS Cut Line= 6
1665570.65409268493151.8832910521665484.06240235493139.191387297
1665410.08289151493126.8613594641665312.16904534493106.069078223
 1665239.0658451493077.4185449641665153.53517626493045.113491462
#Sta/Elev= 30
       0 1092.96      24 1088.14    43.9 1083.49    57.1 1078.89      77 1070.53
    80.3 1068.84    83.6 1065.91    90.3 1055.63    93.6 1052.37  113.171039.604
   116.9 1038.33   120.2 1038.21  130.051039.604   140.2 1040.94     197 1041.14
   278.3 1043.32   285.3 1043.73   292.4 1045.17   300.7 1047.39   306.4 1049.81
   313.4 1054.22   320.5  1059.6   328.5 1064.33   345.2 1070.83   355.7 1075.81
   373.2 1086.91   376.8 1088.71   394.3 1094.25   407.4 1099.87   432.6 1114.11
#Mann= 3 ,-1,0
       0      .1       0  113.17    .045       0  130.05      .1       0
Bank Sta=113.17,130.05
XS Rating Curve= 0 ,0
Exp/Cntr(USF)=0,0
Exp/Cntr=0.3,0.1

Type RM Length L Ch R = 1 ,798     ,198.2,197.8,197
XS GIS Cut Line= 2
1665585.19610084493004.3019031031665168.83591612493004.301903103
#Sta/Elev= 30
       0 1089.84    38.2  1083.8      50 1080.95    67.8 1075.21    74.3 1072.35
    77.6 1069.77    87.5 1060.78    97.3 1050.46  113.781037.475     117 1036.48
   120.3 1036.34  130.211037.478     140 1040.87   143.2 1041.15   149.8 1040.69
     222  1040.6   244.9 1039.94   284.3 1041.34   294.2  1042.7     304 1045.39
   310.6 1048.08   328.3 1058.67   353.2  1072.4   359.8 1076.69   366.3 1081.77
   376.2 1087.71   382.7 1090.27   399.1 1095.52   405.7 1098.74   416.4 1105.43
#Mann= 4 ,-1,0
       0     .05       0      50      .1       0  113.78    .045       0
  130.21      .1       0
Bank Sta=113.78,130.21
XS Rating Curve= 0 ,0
Exp/Cntr(USF)=0,0
Exp/Cntr=0.3,0.1

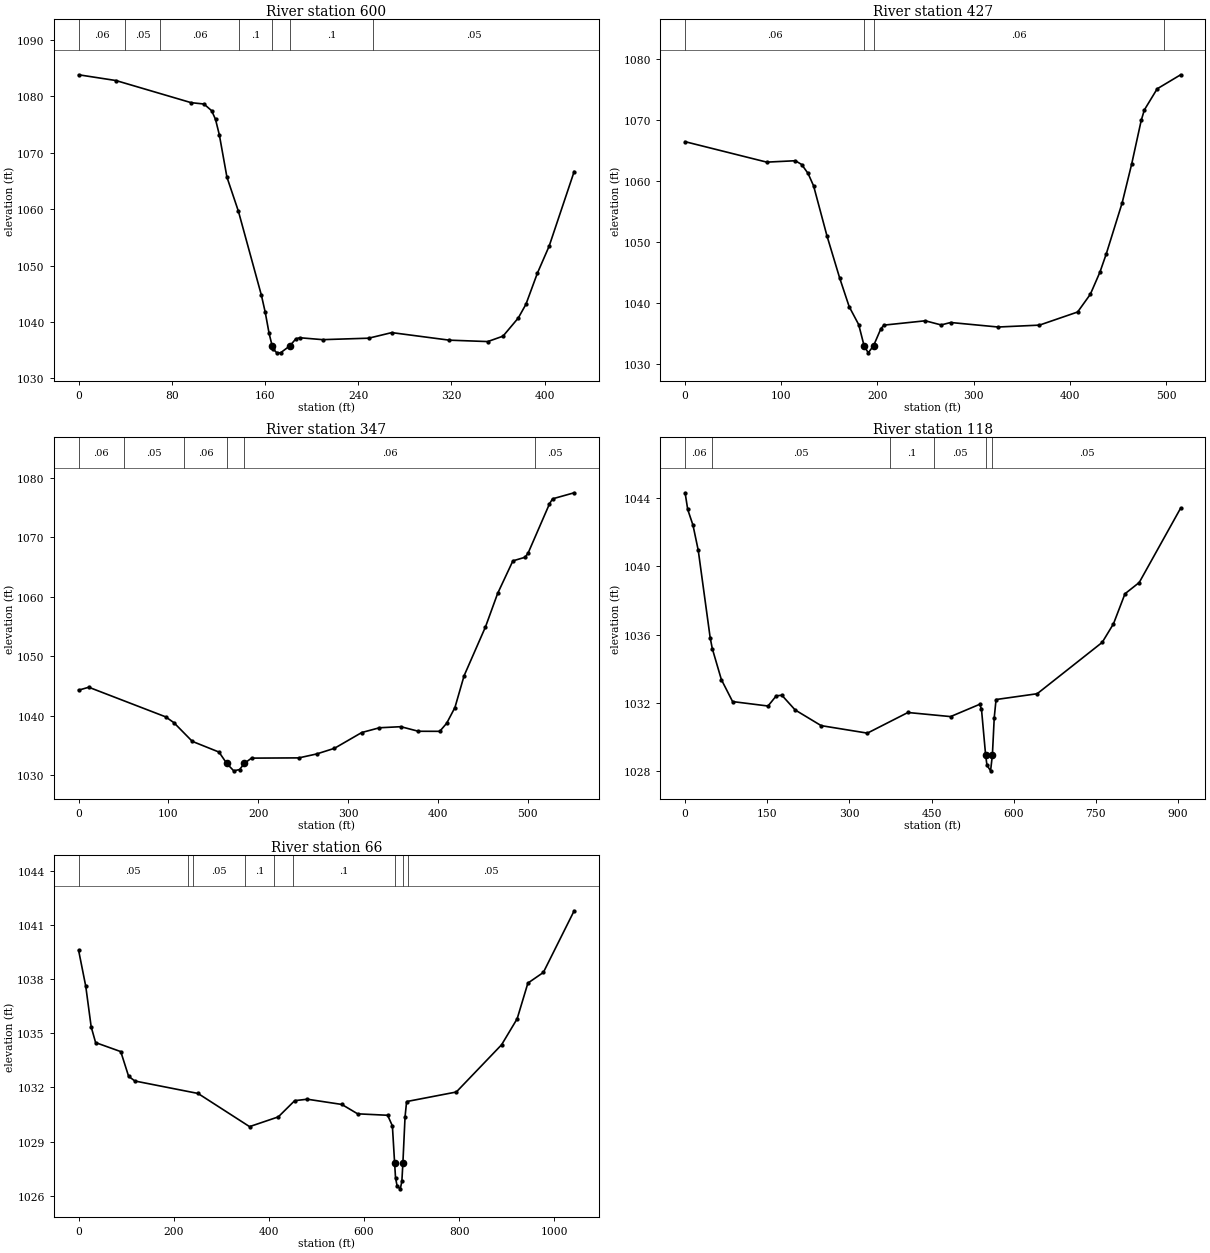
Type RM Length L Ch R = 1 ,600     ,171,172.5,173.6
XS GIS Cut Line= 6
1665641.24991073492798.6527912961665553.78551874492803.959539209
1665478.76204674492807.6639281261665379.06309915492815.661943634
1665304.43529566492823.123214801 1665216.8714944 492826.16421922
#Sta/Elev= 30
       0 1083.85      32 1082.83    96.6  1078.9   107.6 1078.66   114.2 1077.47
   117.5 1075.94   120.8 1073.18   127.3 1065.69   137.2  1059.6   156.9 1044.72
   160.2 1041.69   163.5 1037.96  166.131035.733   166.7 1035.25     170 1034.53
   173.3  1034.5  181.321035.737   186.5 1036.99   189.8 1037.18   209.5 1036.84
     249  1037.1   268.8 1038.09   318.2 1036.75   351.2  1036.5   364.3 1037.46
   377.4 1040.68     384 1043.12   393.8 1048.63   403.9 1053.43   425.4 1066.68
#Mann= 7 ,-1,0
       0     .06       0      40     .05       0      70     .06       0
  137.63      .1       0  166.13    .045       0  181.32      .1       0
  252.74     .05       0
Bank Sta=166.13,181.32
XS Rating Curve= 0 ,0
Exp/Cntr(USF)=0,0
Exp/Cntr=0.3,0.1

Type RM Length L Ch R = 1 ,427     ,82.2,80.9,79.8
XS GIS Cut Line= 6
1665670.97435472492655.2894632281665583.73338746492648.419726303
1665509.06785438492641.3452653941665409.51359155  492631.9138538
1665334.84773039492624.8400490641665158.57599436492646.943869943
#Sta/Elev= 30
       0 1066.39    84.9 1063.04   114.6 1063.27   121.2 1062.65   127.8  1061.2
   133.6 1059.15   147.5 1050.96   160.7 1044.06   170.6 1039.36   180.5 1036.42
  186.061032.975   190.4  1031.8  195.961032.975   203.6 1035.77   206.8 1036.34
   249.7 1037.05   266.2 1036.37   276.1 1036.77   325.5 1036.03   368.4 1036.34
   408.1 1038.49   421.3 1041.39   431.3 1045.02   437.9 1048.02   454.4 1056.37
   464.3 1062.73   474.2 1069.87   477.5  1071.6   490.8 1075.05   515.2 1077.35
#Mann= 4 ,-1,0
       0     .06       0  186.06    .045       0  195.96     .06       0
  497.51     .05       0
Bank Sta=186.06,195.96
XS Rating Curve= 0 ,0
Exp/Cntr(USF)=0,0
Exp/Cntr=0.3,0.1

Type RM Length L Ch R = 1 ,347     ,227.4,228.4,228.2
XS GIS Cut Line= 6
1665679.55976822492577.2084018251665592.31880097  492570.3386649
1665517.65326788492563.2642039911665418.09900505492553.832792397
1665343.43314389492546.758987661 1665136.5021579492601.380194867
#Sta/Elev= 30
       0  1044.3    11.3 1044.79    96.8 1039.81     106 1038.83   126.5 1035.68
   156.2 1033.88  164.891031.958   172.6 1030.72   179.2 1030.94  184.291031.958
   192.4 1032.86   245.1  1032.9   264.9 1033.56   284.7 1034.51   315.1 1037.17
   334.8 1037.97   358.6 1038.15   378.1 1037.38   401.9 1037.37   409.6 1038.73
   418.8 1041.38     429 1046.73   452.8 1054.95   466.3 1060.57   483.3 1066.06
   496.9 1066.67   500.3 1067.39     524 1075.65   527.4  1076.5   551.5 1077.52
#Mann= 6 ,-1,0
       0     .06       0      50     .05       0  117.51     .06       0
  164.89    .045       0  184.29     .06       0  507.51     .05       0
Bank Sta=164.89,184.29
XS Rating Curve= 0 ,0
Exp/Cntr(USF)=0,0
Exp/Cntr=0.3,0.1

Type RM Length L Ch R = 1 ,118     ,52.3,52.3,52.5
XS GIS Cut Line= 5
1665875.01949333492705.1878288141665838.35958851492576.298684212
1665661.70085103492357.7392691621665436.65989169492322.641137889
1665195.10216469492423.806339794
#Sta/Elev= 30
       0 1044.31     4.8 1043.33    14.4 1042.41      24 1040.94    45.8 1035.81
    49.7 1035.17    66.2 1033.36    86.7 1032.07   151.4 1031.81   166.5 1032.41
   176.7 1032.44   200.9 1031.58   248.4 1030.66   332.8 1030.22   406.8 1031.43
   484.7 1031.19   537.8 1031.91   541.1 1031.63548.64941028.937   551.1 1028.34
   557.7 1028.01561.01941028.936   564.4 1031.13   567.7 1032.19   642.8 1032.53
   761.5 1035.54   782.1 1036.63   803.1 1038.39   829.1 1039.05   904.7 1043.41
#Mann= 6 ,-1,0
       0     .06       0      50     .05       0     374      .1       0
  455.03     .05       0548.6494    .045       0561.0194     .05       0
Bank Sta=548.6494,561.0194
XS Rating Curve= 0 ,0
Exp/Cntr(USF)=0,0
Exp/Cntr=0.3,0.1

Type RM Length L Ch R = 1 ,66      ,,,
XS GIS Cut Line= 5
1665946.61509313492742.4996657541665927.82541333492593.503650523
1665649.82942427492303.0274762951665424.78846493492267.929345021
1665183.23073793492369.094546927
#Sta/Elev= 30
       0  1039.6      15 1037.61    26.4 1035.36    35.7 1034.49    88.6 1033.99
   105.1 1032.62   118.3 1032.36     251 1031.67   359.4 1029.83   419.8 1030.37
   454.3 1031.27   480.8 1031.35   553.4 1031.06   586.6 1030.54   649.7 1030.46
   659.7 1029.87 664.4181027.792   666.3 1026.99   669.7 1026.53   676.3 1026.38
   679.6 1026.79 681.7781027.814   686.3 1030.37   689.6 1031.22   794.1 1031.75
   889.3 1034.37     922 1035.81   944.6 1037.79   977.1 1038.38  1041.9  1041.8
#Mann= 9 ,-1,0
       0     .05       0  230.18      .1       0  240.18     .05       0
  350.18      .1       0  410.18     .05       0  450.18      .1       0
 664.418    .045       0 681.778      .1       0  692.24     .05       0
Bank Sta=664.418,681.778
XS Rating Curve= 0 ,0
Exp/Cntr(USF)=0,0
Exp/Cntr=0.3,0.1
LCMann Table=0

Chan Stop Cuts=-1
Use User Specified Reach Order=0
Composite Channel Slope=5